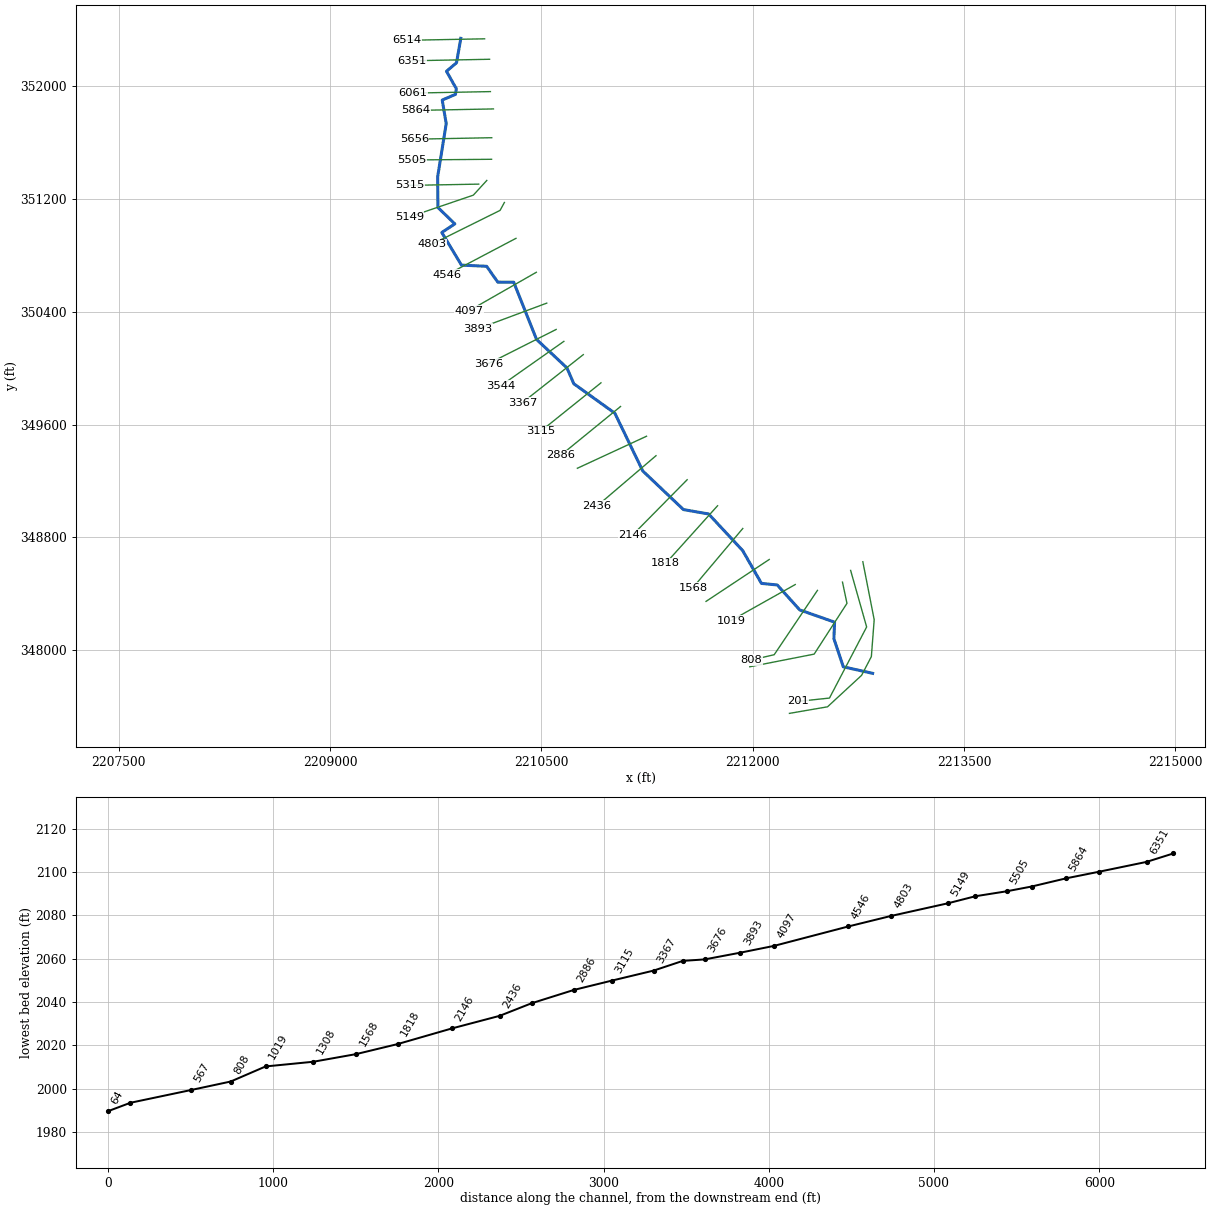
--- SIMMSRN.prj (project) ---

Proj Title=SIMMSRN
Current Plan=p01
Default Exp/Contr=0,0
English Units
Geom File=g01
Flow File=f01
Plan File=p01
BEGIN DESCRIPTION:
Stream Name- Simms Run
Flood Zone: Zone A
Greenbrier County, WV
County-Wide Study
WVDHSEM-2018-3, Flood Risk Project
HEC-RAS Version: 5.0.7
General Notes:
For the Hydrology Regression was used.
END DESCRIPTION:
DSS Export Rating Curves= 0
DSS Export Rating Curve Sorted= 0
DSS Export Volume Flow Curves= 0
DXF OffsetX= 0
DXF OffsetY= 0
DXF ScaleX= 0
DXF ScaleY= 0

--- SIMMSRN.p01 (plan) ---

Plan Title=Floodplain
Program Version=5.07
Short Identifier=Floodplain
Geom File=g01
Flow File=f01
Subcritical Flow
K Sum by GR= 0
Std Step Tol= 0.01
Critical Tol= 0.01
Num of Std Step Trials= 20
Max Error Tol= 0.3
Flow Tol Ratio= 0.001
Split Flow NTrial= 30
Split Flow Tol= 0.02
Split Flow Ratio= 0.02
Log Output Level= 0
Friction Slope Method= 1
Unsteady Friction Slope Method= 2
Unsteady Bridges Friction Slope Method= 1
Parabolic Critical Depth
Global Vel Dist= 0 , 0 , 0
Global Log Level= 0
CheckData=True
Encroach Param=-1 ,0,0, 0
Mapping Interval=1HOUR
Computation Time Step Use Courant=        0
Computation Time Step Use Time Series=    0
Computation Time Step Count To Double=0
Computation Time Step Max Doubling=0
Computation Time Step Max Halving=0
Computation Time Step Residence Courant=0
Run HTab= 0
Run UNet= 0
Run Sediment= 0
Run PostProcess= 0
Run WQNet= 0
Run RASMapper= 0
UNET Theta= 0
UNET Theta Warmup= 0
UNET ZTol= 0
UNET ZSATol= 0
UNET MxIter= 0
UNET Max Iter WO Improvement= 0
UNET MaxInSteps= 0
UNET DtIC= 0
UNET DtMin= 0
UNET MaxCRTS= 0
UNET WFStab= 0
UNET SFStab= 0
UNET WFX= 1
UNET SFX= 1
UNET 1D Methodology=Finite Difference
UNET DSS MLevel= 1
UNET Pardiso=0
UNET DZMax Abort= 0
UNET Use Existing IB Tables= 0
UNET Froude Reduction=False
UNET Froude Limit= 0
UNET Froude Power= 0
UNET D1 Cores= 0
UNET D2 Coriolis=0
UNET D2 Cores= 0
UNET D2 Theta= 1
UNET D2 Theta Warmup= 1
UNET D2 Z Tol= 0.01
UNET D2 Volume Tol= 0.01
UNET D2 Max Iterations= 20
UNET D2 Equation= 0
UNET D2 RampUpFraction=0.1
UNET D2 TimeSlices= 1
UNET D2 BCVolumeCheck=0
UNET D1D2 MaxIter= 0
UNET D1D2 ZTol=0.01
UNET D1D2 QTol=0.1
UNET D1D2 MinQTol=1
Write IC File= 0
Write IC File at Fixed DateTime=0
Write IC File at Sim End=0
Echo Input=False
Echo Parameters=False
Echo Output=False
Write Detailed= 0
HDF Write Warmup=0
HDF Write Time Slices=0
HDF Flush=0
HDF Face Node Velocities=0
HDF Compression= 1
HDF Chunk Size= 1
HDF Spatial Parts= 1
HDF Use Max Rows=0
HDF Fixed Rows= 1
Calibration Method= 0
Calibration Iterations= 20
Calibration Max Change=0.05
Calibration Tolerance=0.2
Calibration Maximum=1.5
Calibration Minimum=0.5
Calibration Optimization Method= 1
WQ AD Non Conservative
WQ ULTIMATE=-1
WQ Max Comp Step=1HOUR
WQ Output Interval=15MIN
WQ Output Selected Increments= 0
WQ Output face flow=0
WQ Output face velocity=0
WQ Output face area=0
WQ Output face dispersion=0
WQ Output cell volume=0
WQ Output cell surface area=0
WQ Output cell continuity=0
WQ Output cumulative cell continuity=0
WQ Output face conc=0
WQ Output face dconc_dx=0
WQ Output face courant=0
WQ Output face peclet=0
WQ Output face adv mass=0
WQ Output face disp mass=0
WQ Output cell mass=0
WQ Output cell source sink temp=0
WQ Output nsm pathways=0
WQ Output nsm derived pathways=0
WQ Output MaxMinRange=-1
WQ Daily Max Min Mean=-1
WQ Daily Range=0
WQ Daily Time=0
WQ Create Restart=0
WQ Fixed Restart=0
WQ System Summary=0
WQ Write To DSS=0
WQ Use Fixed Temperature=0
Sorting and Armoring Iterations= 10
XS Update Threshold= 0.02
Bed Roughness Predictor= 0
Hydraulics Update Threshold= 0.02
Energy Slope Method= 1
Volume Change Method= 1
Sediment Retention Method= 0
XS Weighting Method= 0
Number of US Weighted Cross Sections= 1
Number of DS Weighted Cross Sections= 1
Upstream XS Weight=0
Main XS Weight=1
Downstream XS Weight=0
Number of DS XS's Weighted with US Boundary= 1
Upstream Boundary Weight= 1
Weight of XSs Associated with US Boundary= 0
Number of US XS's Weighted with DS Boundary= 1
Downstream Boundary Weight= 0.5
Weight of XSs Associated with DS Boundary= 0.5
Percentile Method= 0
Sediment Output Level= 3
Mass or Volume Output= 0
Output Increment Type= 1
Profile and TS Output Increment= 1
XS Output Flag= 0
XS Output Increment= 10
Write Gradation File= 0
Read Gradation Hotstart= 0
Write HDF5 File= 1
Write Binary Output= 1
Write DSS Sediment File= 0
SV Curve= 0
Specific Gage Flag= 0

--- SIMMSRN.f01 (steady flow) ---

Flow Title=Flow
Program Version=5.07
Number of Profiles= 6
Profile Names=f1p,f10p,f4p,f2p,f02p,f1pplus
River Rch & RM=Simms Run,Main            ,6514
     534     282     375     452     747     790
River Rch & RM=Simms Run,Main            ,4803
     647     344     456     549     902     957
Boundary for River Rch & Prof#=Simms Run,Main            , 1
Up Type= 0
Dn Type= 3
Dn Slope=0.03
Boundary for River Rch & Prof#=Simms Run,Main            , 2
Up Type= 0
Dn Type= 3
Dn Slope=0.03
Boundary for River Rch & Prof#=Simms Run,Main            , 3
Up Type= 0
Dn Type= 3
Dn Slope=0.03
Boundary for River Rch & Prof#=Simms Run,Main            , 4
Up Type= 0
Dn Type= 3
Dn Slope=0.03
Boundary for River Rch & Prof#=Simms Run,Main            , 5
Up Type= 0
Dn Type= 3
Dn Slope=0.03
Boundary for River Rch & Prof#=Simms Run,Main            , 6
Up Type= 0
Dn Type= 3
Dn Slope=0.03
DSS Import GetInterval= 0
DSS Import GetPeak= 0
DSS Import FillOption= 0

--- SIMMSRN.g01 (geometry) ---

Geom Title=Geometry
Program Version=5.07

River Reach=Simms Run       ,Main
Reach XY= 30
 2209927.4481229352341.2183667922209897.18407583352167.747585138
  2209825.869914352107.3251338062209895.84024648351983.343754476
2209889.41063641351943.3763524912209795.59540869351903.169826325
2209823.97648599351736.0368155952209763.39300481351359.622889047
2209764.87462918351140.5665686332209885.19919165351024.149806714
2209792.56158165350963.0114775652209932.16527008 350731.42414566
2210110.84069629350723.1775875282210190.00765436350610.474626381
2210303.26038605 350610.199741112210464.71181216350204.369950211
2210680.99221953350001.7975207182210729.53739802349889.561196646
2211020.90197275349680.2886493112211218.92191794349270.666437065
2211507.80703383348996.1786180222211686.28763966 348965.17494471
2211928.33749382348705.1121219752212061.54392032348472.240212386
2212173.75981075348460.9990866292212333.16903325348284.094919389
2212580.46732367348197.2665730022212575.86958914348079.449625885
2212642.53673971 347880.022891012212850.87276248347833.879531438

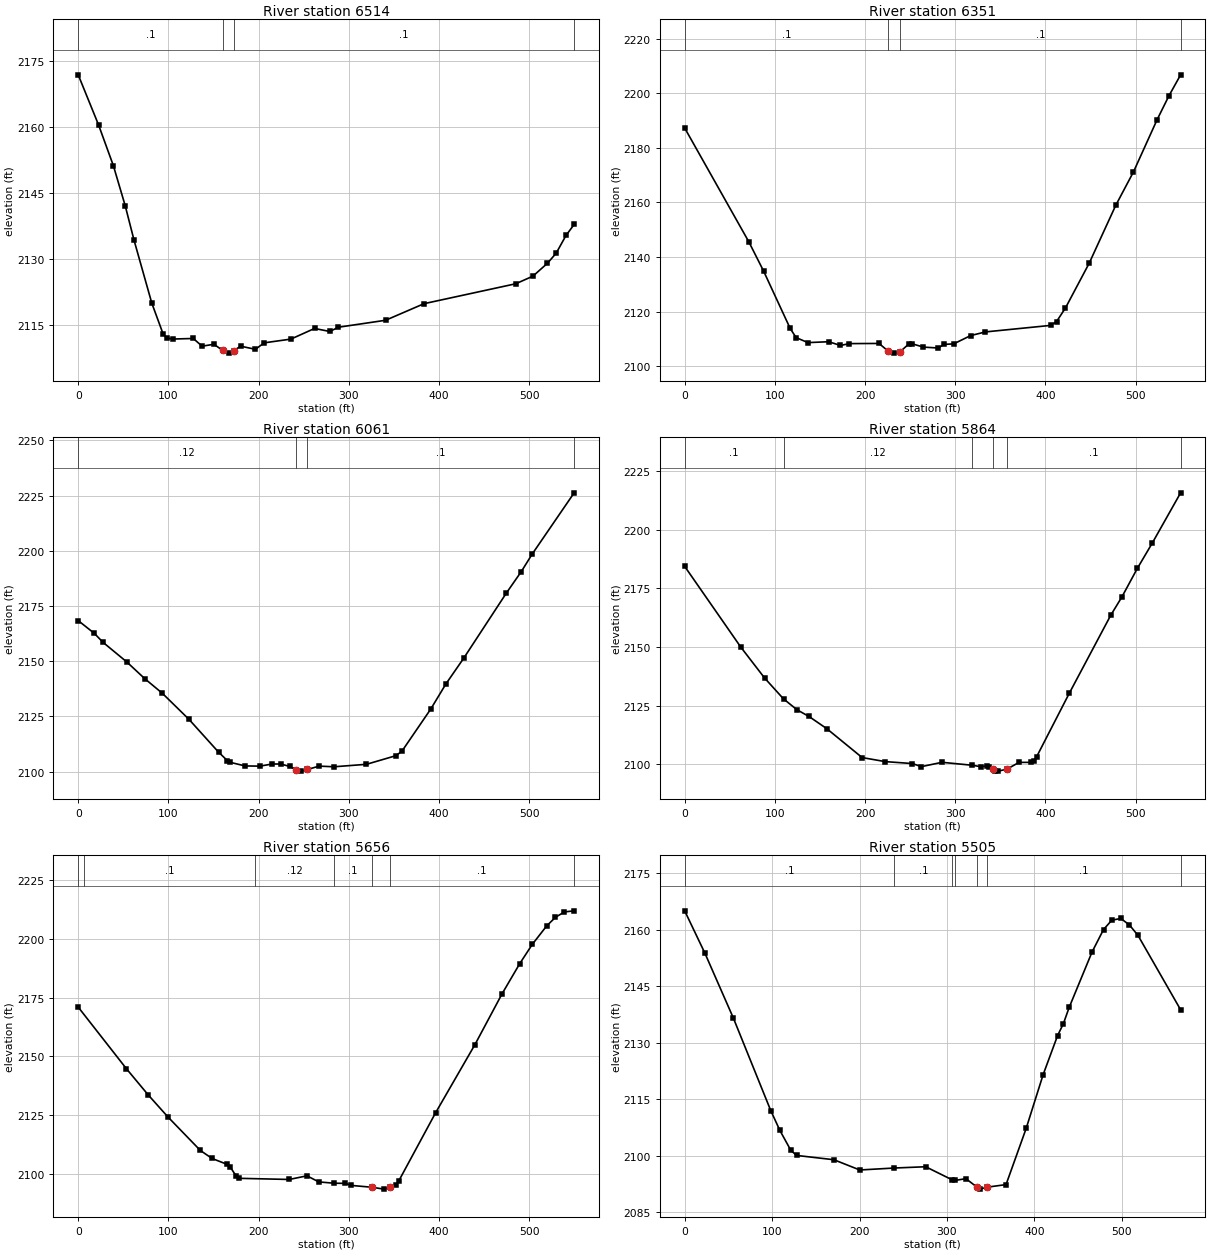
Type RM Length L Ch R = 1 ,6514    ,161.9,162.6,162.3
XS GIS Cut Line= 2
2210096.48494558352337.8343073932209546.58727327352327.225349085
#Sta/Elev= 30
       0 2171.93    22.6 2160.53      39 2151.27    52.1 2142.19    61.9 2134.35
    81.6 2120.04      94 2113.11      98 2112.14   104.6 2111.87   127.6    2112
   137.4 2110.25   150.5 2110.68   160.4 2109.27     167 2108.67   172.7 2109.26
   180.1 2110.25   196.5 2109.54   206.3 2111.01   235.9 2111.86   262.1 2114.28
     279 2113.59   288.6 2114.56   340.9 2116.14   383.5 2119.91   485.3 2124.44
   504.3 2126.17   520.4  2129.1   530.1  2131.4     541 2135.43     550 2137.92
#Mann= 4 ,-1 , 0
       0      .1       0   160.4    .045       0   172.7      .1       0
     550      .1       0
Bank Sta=160.4,172.7
XS Rating Curve= 0 ,0
Exp/Cntr=0.3,0.1

Type RM Length L Ch R = 1 ,6351    ,288.9,289.9,288.5
XS GIS Cut Line= 2
2210131.87831185352192.5994754262209581.98063955352181.990517118
#Sta/Elev= 30
       0 2187.32    71.1  2145.6    87.5 2134.86     117  2113.8   123.6 2110.44
   136.7 2108.61   159.7 2108.93   172.8 2107.56   182.7 2108.24   215.5  2108.3
   225.9 2105.43   231.9 2104.75   238.8 2105.25   248.4 2108.04   251.6 2108.24
   264.7 2106.96   281.1 2106.63   287.7 2107.96   298.3 2108.14   317.2 2111.19
   333.6 2112.53   405.8 2114.92   412.4 2116.32   422.3 2121.32   448.5 2137.66
     478 2158.91   497.7 2171.22   523.9 2190.35   537.1 2199.16     550 2206.82
#Mann= 4 ,-1 , 0
       0      .1       0   225.9    .045       0   238.8      .1       0
     550      .1       0
Bank Sta=225.9,238.8
XS Rating Curve= 0 ,0
Exp/Cntr=0.3,0.1

Type RM Length L Ch R = 1 ,6061    ,192.9,197,194.7
XS GIS Cut Line= 2
2210137.63251928351963.1489683622209587.73484698351952.540010054
#Sta/Elev= 30
       0 2168.36    17.8  2162.6    27.6 2158.49    53.9 2149.62    73.6 2142.13
    93.3 2135.43   122.8 2123.64   155.6 2108.79   165.5  2104.9   168.7 2104.14
   185.1 2102.52   201.5 2102.43   214.7 2103.37   224.5 2103.41   234.4 2102.31
   241.4 2100.82   247.1 2100.17   254.1 2100.91   267.2 2102.44   283.6 2102.14
   319.7 2103.26   352.5 2107.19   359.1 2109.26     391 2128.31   407.7 2139.62
     428 2151.62   474.6 2180.71   491.4 2190.59   503.4 2198.46     550 2226.25
#Mann= 4 ,-1 , 0
       0     .12       0   241.4    .045       0   254.1      .1       0
     550      .1       0
Bank Sta=241.4,254.1
XS Rating Curve= 0 ,0
Exp/Cntr=0.3,0.1

Type RM Length L Ch R = 1 ,5864    ,207.4,208.4,206.8
XS GIS Cut Line= 2
2210159.17245541351840.1248722282209609.27478311 351829.51591392
#Sta/Elev= 30
       0 2184.41    62.3 2149.97    88.6 2136.85   109.6 2127.94   124.6  2123.3
   137.8 2120.46   157.5 2115.28   196.8 2102.94   222.3 2101.22   252.6 2100.38
   262.5 2099.07   285.4 2100.92   318.9 2099.66   328.1 2099.08     335 2099.36
   337.9 2099.11   341.4 2098.09   344.5 2097.27   347.7 2097.16   357.5 2098.01
   370.8 2100.89   383.9 2100.89   387.2 2101.67   390.4 2103.35   426.5 2130.32
   472.5 2163.58   484.9  2171.4     502 2183.55   518.5  2194.3     550 2215.75
#Mann= 6 ,-1 , 0
       0      .1       0   109.6     .12       0   318.9     .12       0
   341.4    .045       0   357.5      .1       0     550      .1       0
Bank Sta=341.4,357.5
XS Rating Curve= 0 ,0
Exp/Cntr=0.3,0.1

Type RM Length L Ch R = 1 ,5656    ,151.2,151.2,150.7
XS GIS Cut Line= 2
2210147.11454132351635.8433278292209597.21686902351625.234369521
#Sta/Elev= 30
       0 2170.98    53.5  2144.7    77.6 2133.56    99.5 2124.15   135.5 2109.85
   148.5 2106.44   165.1 2103.95   168.4 2102.91   174.9  2099.1   178.2 2097.99
     234  2097.5   253.7 2099.05   266.8 2096.46   283.7  2095.9   296.3 2095.84
   302.9 2094.96   326.3 2094.16     339 2093.38   345.6 2094.13   352.1 2095.01
   355.4 2096.81   396.3  2125.9     440 2155.02   470.1  2176.7   489.7 2189.55
   503.6 2197.75   519.5 2205.59   529.3 2209.29   539.2 2211.57     550 2212.04
#Mann= 7 ,-1 , 0
       0      .1       0    6.35      .1       0   196.1     .12       0
   283.7      .1       0   326.3    .045       0   345.6      .1       0
     550      .1       0
Bank Sta=326.3,345.6
XS Rating Curve= 0 ,0
Exp/Cntr=0.3,0.1

Type RM Length L Ch R = 1 ,5505    ,190.7,190.1,190.5
XS GIS Cut Line= 2
2210146.21527307351482.653219969 2209578.9660662 351477.86633674
#Sta/Elev= 30
       0 2165.04    23.1 2153.82    55.8 2136.52    98.5    2112   108.9 2106.76
   121.5 2101.44   128.1 2100.12   170.7 2098.98   200.3 2096.26   239.6 2096.78
   275.7 2097.12   306.3 2093.61   309.6  2093.5   321.7 2093.96   334.8 2091.63
   338.1 2091.18   345.4 2091.68   367.6 2092.38   390.6 2107.28     410 2121.54
   426.6 2131.95   433.2 2135.09   439.8  2139.4     466 2154.12   479.1 2160.07
   488.5 2162.54   498.8 2163.02   508.7  2161.3   518.5 2158.53   567.3 2138.78
#Mann= 7 ,-1 , 0
       0      .1       0   239.6      .1       0   306.3     .12       0
   309.6     .12       0   334.8    .045       0   345.4      .1       0
   567.3      .1       0
Bank Sta=334.8,345.4
XS Rating Curve= 0 ,0
Exp/Cntr=0.3,0.1

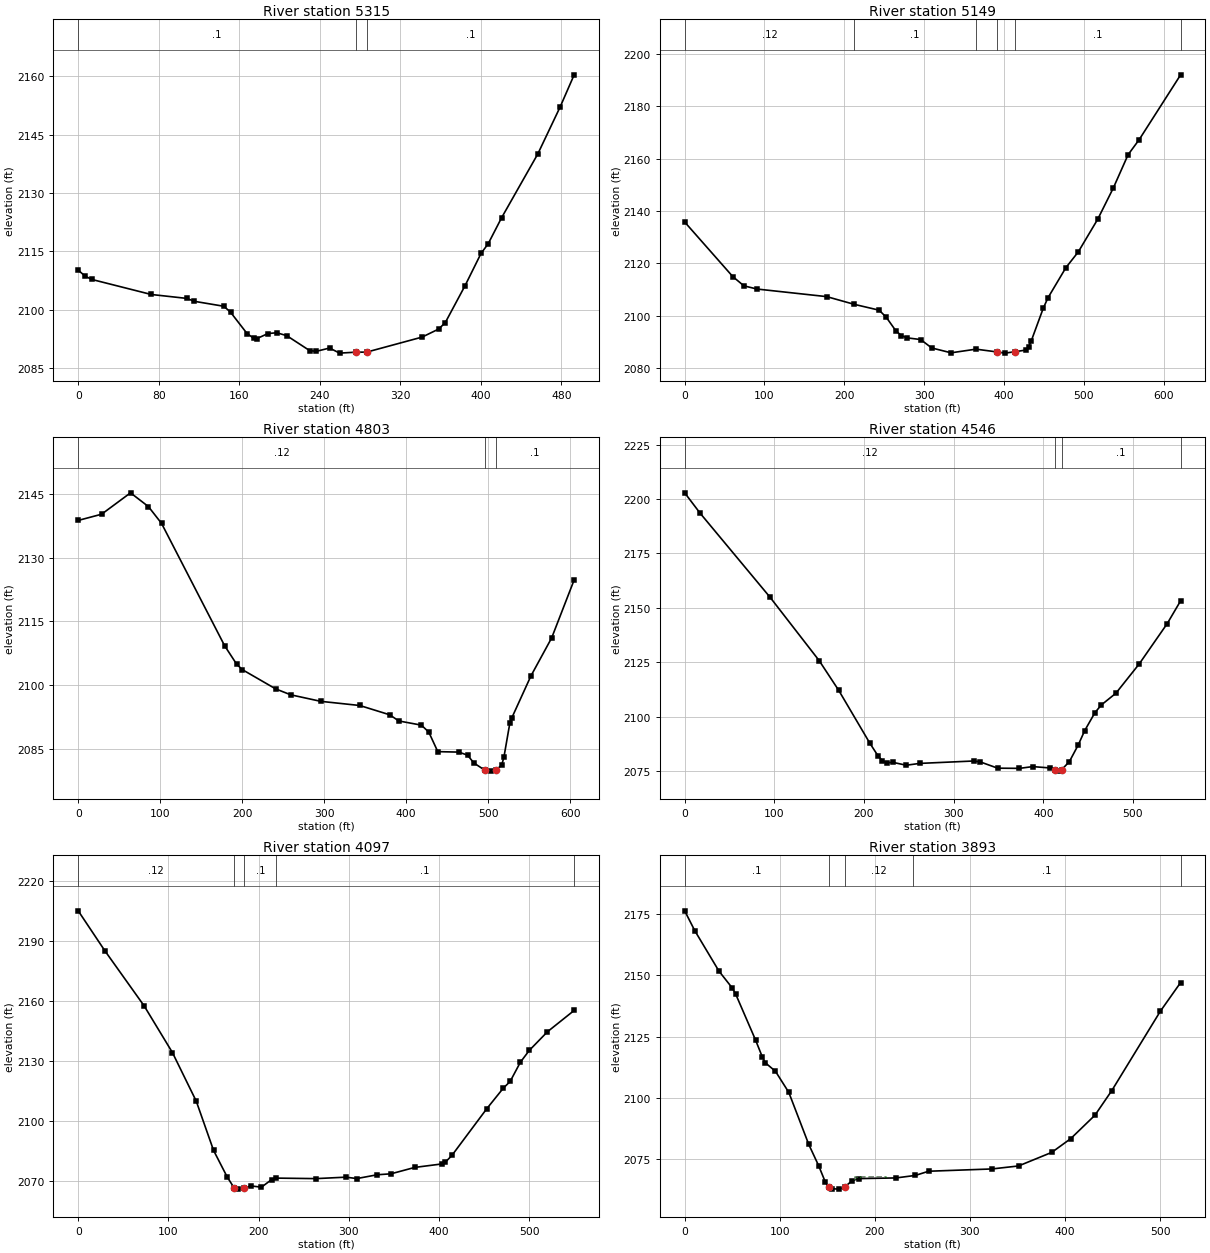
Type RM Length L Ch R = 1 ,5315    ,158.6,165.3,166
XS GIS Cut Line= 2
2210054.58134582351306.3310828442209562.07775331 351297.43041551
#Sta/Elev= 30
       0 2110.19     6.9 2108.64    13.5  2107.8    72.5 2103.94   107.9 2102.93
   115.2 2102.19   144.7 2100.91   151.3 2099.39   167.7 2093.91   174.3  2092.7
   177.5 2092.62   188.5 2093.91   197.2 2094.11   207.1 2093.37     230 2089.51
   236.6 2089.35   249.7 2090.19   259.6 2088.88   275.5 2089.12   286.5 2089.14
   341.6    2093     358 2095.06   364.6 2096.72   384.3 2106.23   400.1 2114.48
   407.2 2116.96   420.5 2123.63   456.5 2140.03   478.6 2152.05   492.6 2160.34
#Mann= 3 , 0 , 0
       0      .1       0   275.5    .045       0   286.5      .1       0
Bank Sta=275.5,286.5
XS Rating Curve= 0 ,0
Exp/Cntr(USF)=0,0
Exp/Cntr=0.3,0.1

Type RM Length L Ch R = 1 ,5149    ,347.8,346.7,347.2
XS GIS Cut Line= 3
2210112.04355519351332.481567016 2210016.3854837351228.116690131
2209562.19090046351073.398451739
#Sta/Elev= 30
       0 2135.77    60.3  2114.9    74.2 2111.37    90.5 2110.15     178 2107.24
   212.5 2104.29   243.7 2102.06   252.7  2099.3   264.5 2094.22   271.4 2092.37
   278.4 2091.49   295.7 2090.83   309.5 2087.62   333.8 2085.76     365 2087.16
   391.2  2086.1   401.3 2085.64   413.5 2086.16   427.4 2086.81   430.9 2088.07
   434.3 2090.35   449.2 2102.73   455.1 2106.74   477.6  2118.3   493.2 2124.36
   517.5 2136.82   537.1  2148.8   555.6 2161.52   569.5 2167.28   621.4 2192.05
#Mann= 6 ,-1 , 0
       0     .12       0   212.5      .1       0     365      .1       0
   391.2    .045       0   413.5      .1       0   621.4      .1       0
Bank Sta=391.2,413.5
XS Rating Curve= 0 ,0
Exp/Cntr=0.3,0.1

Type RM Length L Ch R = 1 ,4803    ,255.5,257,255.7
XS GIS Cut Line= 3
2210236.92534456351175.9133534672210206.17087405351119.996134343
2209721.55497497350879.552092107
#Sta/Elev= 30
       0  2138.8    28.5 2140.26    63.8  2145.3    85.6 2142.06   101.6 2138.11
   178.5  2109.3   193.1 2104.97     200 2103.67   240.8 2099.12   259.1 2097.73
   295.7 2096.19   343.3 2095.21   379.9 2093.02   390.9 2091.57   418.5 2090.58
   427.5 2088.95   438.5 2084.34   464.2 2084.23   474.8 2083.51   482.5 2081.67
   496.2 2079.93   503.6 2079.75   509.1 2079.94   516.4 2081.18   519.1 2082.99
   526.4 2091.09   528.6 2092.22   552.1 2102.18   577.4 2111.14   604.8 2124.79
#Mann= 3 , 0 , 0
       0     .12       0   496.2    .045       0   509.1      .1       0
Bank Sta=496.2,509.1
XS Rating Curve= 0 ,0
Exp/Cntr=0.3,0.1

Type RM Length L Ch R = 1 ,4546    ,447.5,449,445.9
XS GIS Cut Line= 2
2210318.93726595350921.4900064512209829.60171635350663.500165052
#Sta/Elev= 30
       0 2202.86    17.4  2193.4    95.3 2154.82     150 2125.73   171.8 2112.07
   206.5 2087.79   215.5 2082.03   220.4 2079.72   225.2 2078.76   232.5 2078.94
   247.1 2077.63   262.2 2078.47   322.4 2079.58   329.7 2079.16   349.1 2076.28
   373.4 2076.19   388.3    2077   407.4 2076.38   412.82075.569   417.1 2074.92
   420.6 2075.62   429.1 2079.29     439 2086.95   446.2 2093.54   457.7 2101.86
   464.8 2105.35     481 2110.73     507 2124.19   538.3 2142.77   553.2 2153.21
#Mann= 4 ,-1 , 0
       0     .12       0   412.8    .045       0   420.6      .1       0
   553.2      .1       0
#XS Ineff= 2 , 0
          319.44 2079.47
Permanent Ineff=
       F       F
Bank Sta=412.8,420.6
XS Rating Curve= 0 ,0
Exp/Cntr=0.3,0.1

Type RM Length L Ch R = 1 ,4097    ,204.3,203.6,202.1
XS GIS Cut Line= 2
2210463.57276265350680.6913269822209986.06189791350407.774903768
#Sta/Elev= 30
       0 2205.07    29.4 2185.21    73.2  2157.5   104.5 2134.21   130.9 2109.93
   150.1 2085.32   165.4 2071.88   172.9 2066.61   176.7 2065.96   184.3 2066.66
   191.8 2067.55   203.2 2066.93   214.5 2070.74   219.9 2071.47   263.6 2071.21
   296.8 2071.94     309 2071.24   331.7 2073.15   346.8 2073.61   373.2 2076.81
   403.5 2078.56   407.2 2079.46   414.4 2082.79   453.1 2106.16   471.5 2116.47
     479 2119.77   490.4 2129.42   500.3 2135.32   520.4 2144.63     550 2155.28
#Mann= 5 ,-1 , 0
       0     .12       0   172.9    .045       0   184.3      .1       0
  219.55      .1       0     550     .12       0
Bank Sta=172.9,184.3
XS Rating Curve= 0 ,0
Exp/Cntr=0.3,0.1

Type RM Length L Ch R = 1 ,3893    ,215.3,216.5,216.9
XS GIS Cut Line= 2
2210537.41443787350461.6135448562210048.67070684 350279.37394017
#Sta/Elev= 30
       0 2176.36    10.6 2168.28      36  2151.8      50  2144.9    53.5 2142.52
    74.5 2123.69    81.5 2116.91    84.6 2114.45    95.5 2110.89   109.5  2102.3
   130.5 2081.06     141 2072.31     148 2065.62   151.5 2063.64     155    2063
     162 2062.83   168.1 2063.63     176 2066.25     183 2067.12   222.3  2067.4
   242.6 2068.42   256.6 2070.13   323.1 2071.06   351.1 2072.28   386.1 2077.83
     406 2083.42   431.5 2092.98   449.2 2103.02   500.3 2135.41   521.6  2147.1
#Mann= 5 ,-1 , 0
       0      .1       0   151.5    .045       0   168.1     .12       0
  240.17      .1       0   521.6      .1       0
#XS Ineff= 1 ,-1
  179.56  212.23 2067.61
Permanent Ineff=
       F
Bank Sta=151.5,168.1
XS Rating Curve= 0 ,0
Exp/Cntr=0.3,0.1

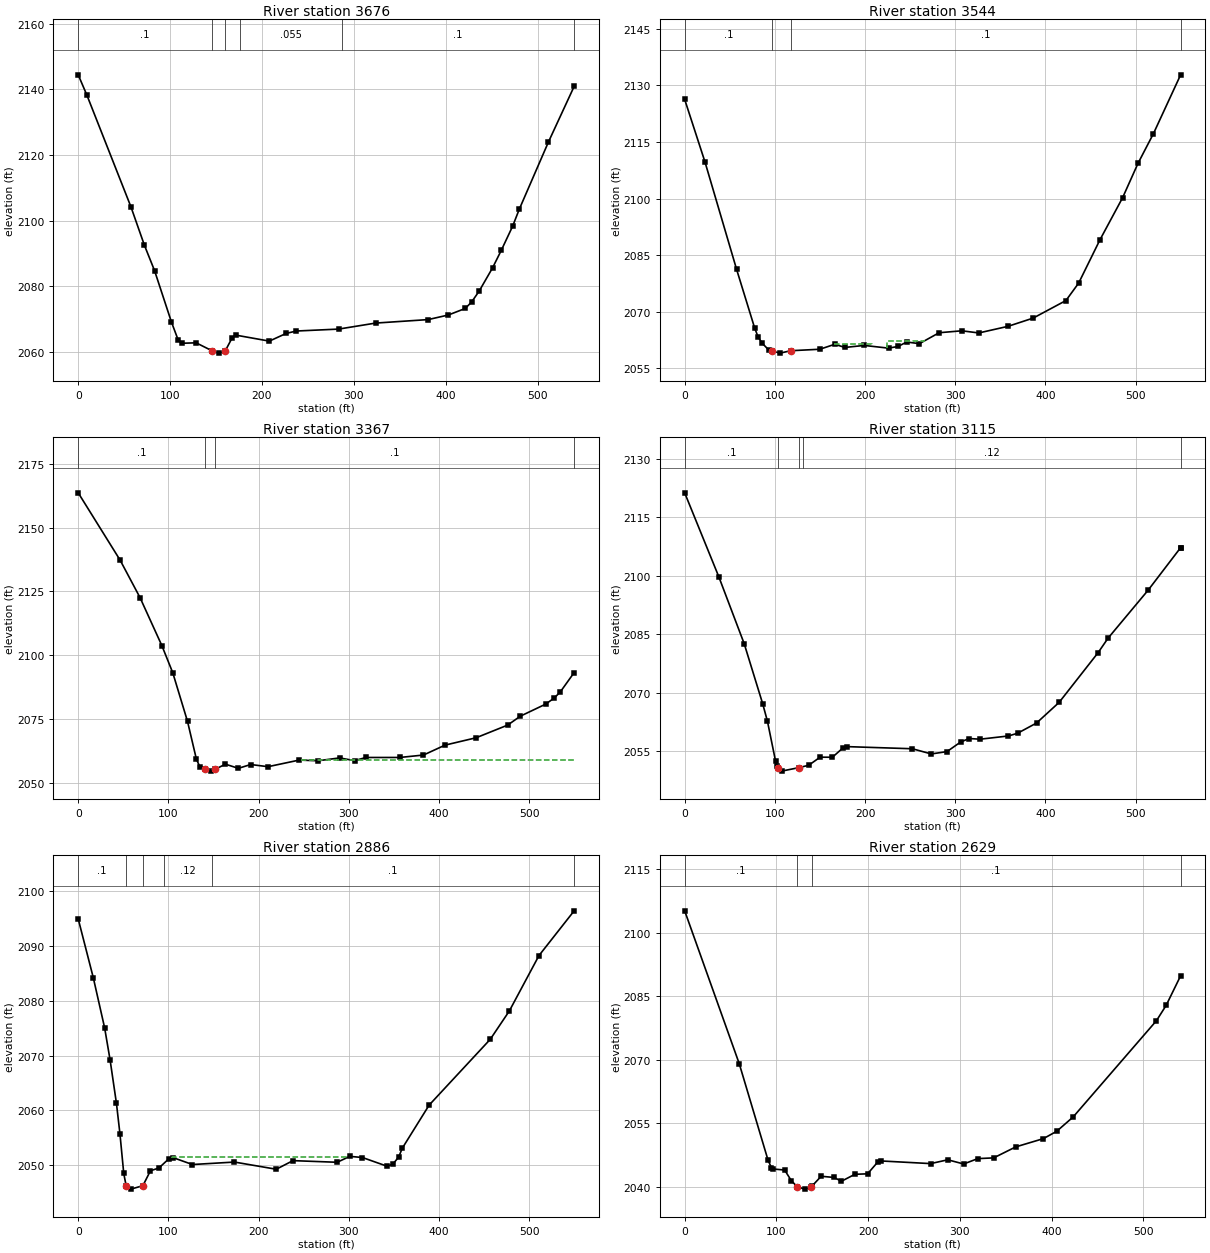
Type RM Length L Ch R = 1 ,3676    ,130.3,132.5,130.3
XS GIS Cut Line= 2
2210604.11508348 350274.714171912210122.29504536350031.474268718
#Sta/Elev= 30
       0 2144.44     9.6 2138.15    57.3  2104.3    72.1 2092.51    83.1 2084.81
   101.4 2069.22   108.8 2063.69   112.5 2062.71   128.3 2062.85   145.4 2060.46
   152.7 2059.71   160.2 2060.49   167.6  2064.4   171.3  2065.2     208 2063.37
   226.4 2065.72   237.4 2066.44   283.4 2067.03   323.7 2068.86   380.8 2069.92
   402.8 2071.32   421.2 2073.31   428.1 2075.28   436.3 2078.58   450.9 2085.67
   460.5 2091.06   472.7 2098.32     480 2103.53   511.7 2123.98   539.7 2140.92
#Mann= 6 ,-1 , 0
       0      .1       0   145.4    .045       0   160.2      .1       0
  176.54    .055       0  287.18      .1       0   539.7      .1       0
#XS Ineff= 1 ,-1
  174.08  224.99 2064.17
Permanent Ineff=
       F
Bank Sta=145.4,160.2
XS Rating Curve= 0 ,0
Exp/Cntr=0.3,0.1

Type RM Length L Ch R = 1 ,3544    ,175.1,176.6,177.4
XS GIS Cut Line= 2
2210659.06886225350190.2592247122210209.26251983349873.756058346
#Sta/Elev= 30
       0 2126.29    22.5 2109.72    57.6 2081.21    77.6 2065.68    81.3 2063.39
    85.7 2061.72    93.1 2059.88      972059.614   105.7 2059.02   117.8 2059.66
   149.9 2060.05   166.4 2061.36   177.8 2060.53   199.1 2061.06   226.1 2060.34
   236.8  2060.8   246.2 2061.97   260.3 2061.53   282.2 2064.43   307.4 2064.94
   326.2 2064.37   358.5 2066.12   386.5 2068.31   422.8 2072.96   436.9 2077.58
   460.5 2089.05   485.7 2100.25   502.8 2109.37   519.9 2117.24     550 2132.81
#Mann= 4 ,-1 , 0
       0      .1       0      97    .045       0   117.8      .1       0
     550      .1       0
#XS Ineff= 2 ,-1
  165.91   207.7 2061.38  224.42  266.97 2062.23
Permanent Ineff=
       F       F
Bank Sta=97,117.8
XS Rating Curve= 0 ,0
Exp/Cntr=0.3,0.1

Type RM Length L Ch R = 1 ,3367    ,251.6,252.4,251.8
XS GIS Cut Line= 2
2210796.98118479350096.1218186432210364.97651737349755.722101653
#Sta/Elev= 30
       0  2163.7    46.5 2137.28    68.5 2122.64    92.8 2103.75   104.9 2093.09
   121.2 2074.07   131.1 2059.17   135.2 2056.04   140.5 2055.28   147.8 2054.54
     152  2055.3   163.3 2057.26   177.6 2055.64   191.3 2057.13   210.5 2056.28
     245 2058.87   266.1 2058.61   289.8 2059.72   306.5 2058.66   319.1 2059.89
   356.7  2059.9   382.9 2060.85   406.8 2064.74   441.3 2067.63   476.3  2072.6
   490.3 2076.09   518.4 2080.82   527.9 2083.21   534.7 2085.64     550  2093.2
#Mann= 4 ,-1 , 0
       0      .1       0   140.5    .045       0     152      .1       0
     550      .1       0
#XS Ineff= 2 , 0
                          246.55         2058.86
Permanent Ineff=
       F       F
Bank Sta=140.5,152
XS Rating Curve= 0 ,0
Exp/Cntr=0.3,0.1

Type RM Length L Ch R = 1 ,3115    ,227.9,229.5,229.1
XS GIS Cut Line= 2
2210922.60977658349896.0729417492210493.83219227349551.617163458
#Sta/Elev= 30
       0 2121.33    37.8 2099.82      66 2082.62    86.6 2067.14    91.8  2062.7
   100.8 2052.46   102.3 2051.36   103.9 2050.85   107.5 2049.92   126.5 2050.81
   137.5 2051.42   150.2  2053.5   163.8 2053.48   175.4 2055.85   179.6 2056.21
   252.5 2055.66   273.5 2054.33   290.9 2054.93   305.9 2057.37   315.5 2058.29
   327.5 2058.11     359 2058.94   369.2 2059.64   390.2 2062.26   415.3 2067.57
   458.5 2080.32   469.5 2084.03   513.9 2096.33     550 2107.26     550 2107.28
#Mann= 5 ,-1 , 0
       0      .1       0   103.9    .045       0   126.5      .1       0
  131.19     .12       0     550      .1       0
Bank Sta=103.9,126.5
XS Rating Curve= 0 ,0
Exp/Cntr=0.3,0.1

Type RM Length L Ch R = 1 ,2886    ,258.2,256.2,253.5
XS GIS Cut Line= 2
2211061.19928448349727.8252599122210635.04594882349380.128071967
#Sta/Elev= 30
       0 2094.93    16.7 2084.22    29.3 2075.05    35.4 2069.15    42.4 2061.27
    46.3 2055.69    50.5 2048.48    53.1 2046.28    58.3 2045.62    71.7 2046.24
    80.1 2048.97    89.5 2049.48   100.6 2051.17   105.3 2051.36   126.7 2050.11
   173.3 2050.56   219.6 2049.25   238.2 2050.82   287.2 2050.52   301.2  2051.6
   315.2 2051.39   342.7 2049.79     349  2050.2   355.4 2051.47   359.3 2053.06
   389.2 2060.96     457 2072.97   478.2 2078.16     511 2088.25     550 2096.41
#Mann= 6 ,-1 , 0
       0      .1       0    53.1    .045       0    71.7      .1       0
   95.28     .12       0  148.64      .1       0     550      .1       0
#XS Ineff= 1 ,-1
  104.19  299.48 2051.53
Permanent Ineff=
       F
Bank Sta=53.1,71.7
XS Rating Curve= 0 ,0
Exp/Cntr=0.3,0.1

Type RM Length L Ch R = 1 ,2629    ,188.9,193.3,194.2
XS GIS Cut Line= 2
2211245.64468367349516.7901722062210755.09157512349289.639161666
#Sta/Elev= 30
       0 2105.22    59.5 2069.09    90.9 2046.29    94.5 2044.57    96.5 2044.23
     109 2043.98   116.2 2041.48   122.72040.029   130.7 2039.47   137.9 2040.01
   138.5 2040.13   148.8 2042.51   163.2 2042.22   170.7 2041.31   185.5 2042.97
   199.4 2043.09   210.2 2045.81   213.8 2046.13   268.1  2045.5   286.8  2046.4
   304.1 2045.41   319.5 2046.68   336.8 2046.85   360.9 2049.45     391  2051.4
   405.5 2053.13   423.5 2056.53   514.2 2079.25   524.8 2082.87   540.6 2089.87
#Mann= 4 ,-1 , 0
       0      .1       0   122.7    .045       0   138.5      .1       0
   540.6      .1       0
Bank Sta=122.7,137.9
XS Rating Curve= 0 ,0
Exp/Cntr=0.3,0.1

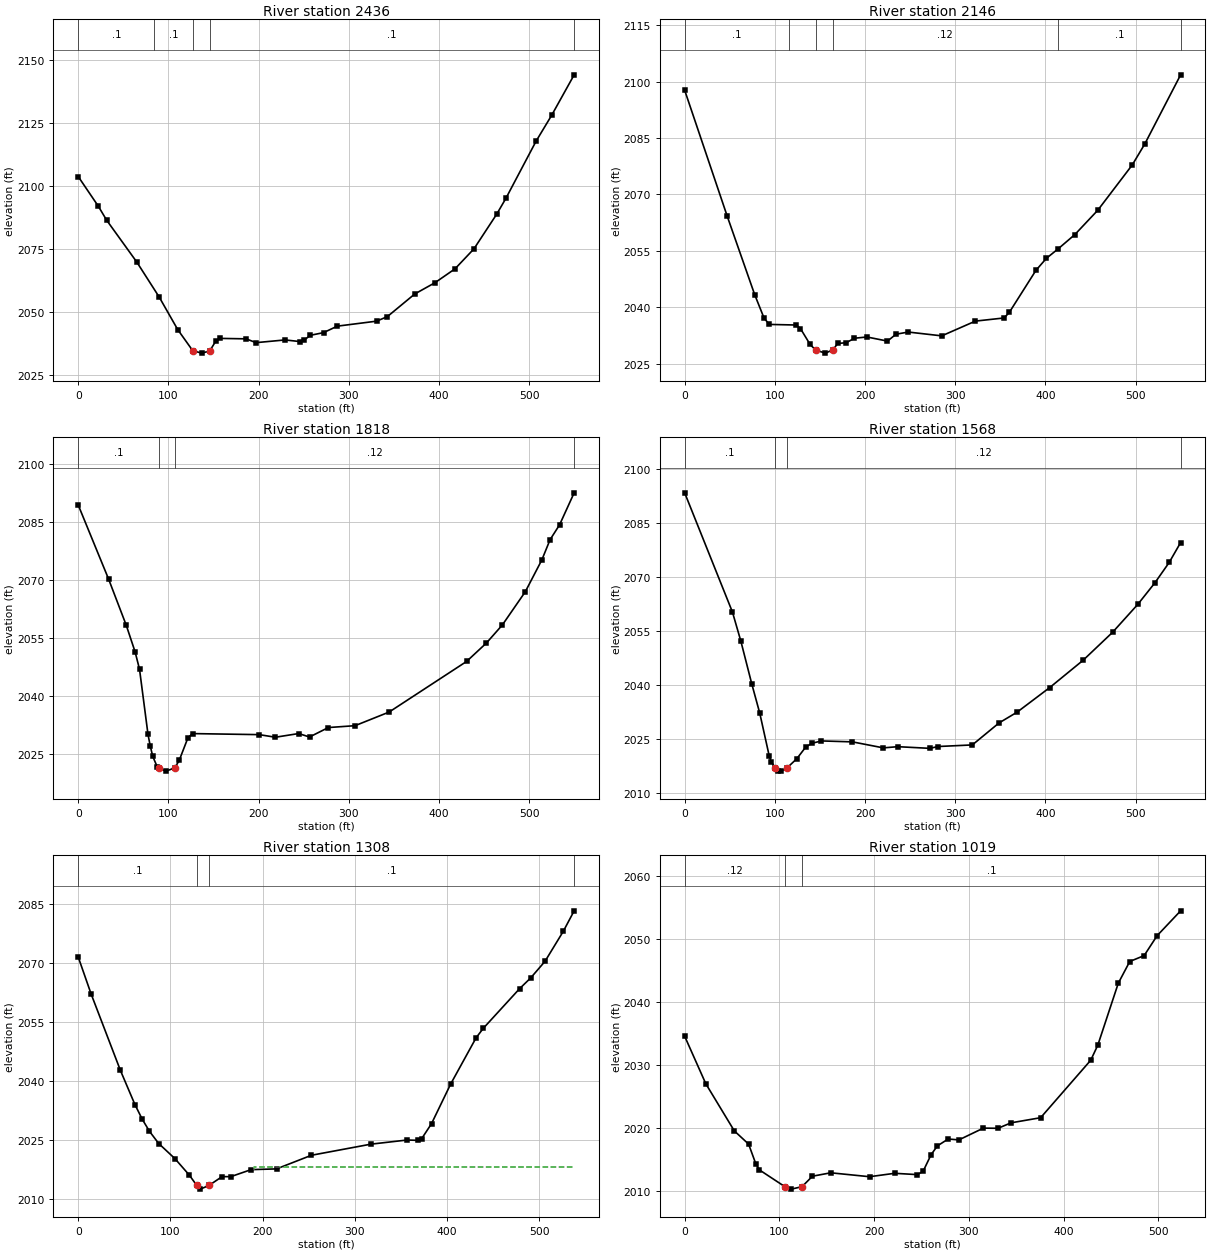
Type RM Length L Ch R = 1 ,2436    ,288.8,290.2,290.6
XS GIS Cut Line= 2
2211313.17657689349378.793379726  2210894.855744349021.711203235
#Sta/Elev= 30
       0 2103.77    22.3 2091.98    31.6  2086.4      65  2069.8    89.8 2055.92
   110.4 2042.97     127 2034.63   136.9 2033.65   145.8 2034.49   152.6 2038.43
   157.3  2039.5   186.2 2039.32   197.2 2037.81   229.4 2038.89   245.7 2038.25
   250.4 2038.79   257.6 2040.74   272.1 2041.79   287.3 2044.36     331 2046.35
   342.9 2048.16   373.2 2057.13   395.7 2061.62   417.9 2067.13   438.9 2075.07
   464.2 2088.88   474.3 2095.11   507.8 2117.83     525 2128.06     550 2144.16
#Mann= 5 ,-1 , 0
       0      .1       0   84.45      .1       0     127    .045       0
   145.8      .1       0     550      .1       0
#XS Ineff= 1 ,-1
  183.51   263.3 2039.16
Permanent Ineff=
       F
Bank Sta=127,145.8
XS Rating Curve= 0 ,0
Exp/Cntr=0.3,0.1

Type RM Length L Ch R = 1 ,2146    ,318.1,328.3,322
XS GIS Cut Line= 2
2211534.27246675 349208.136745712211147.82989895 348816.77739448
#Sta/Elev= 30
       0 2097.68    47.2 2064.19    77.6 2043.38    88.1 2037.08    93.9 2035.44
   123.7 2035.28   128.4 2034.33   139.1 2030.12   145.32028.607     156 2027.81
     164 2028.63   169.9 2030.39   179.1 2030.57   188.3 2031.77   202.1  2032.1
   224.9 2031.01   234.4 2032.84     248 2033.41   285.1  2032.4   322.4 2036.32
   354.3 2037.16   360.1 2038.67   389.6 2049.83   401.2 2053.02   414.2 2055.53
   432.7 2059.32   458.1 2065.78   496.4 2077.84   510.3 2083.42     550 2101.78
#Mann= 6 ,-1 , 0
       0      .1       0  115.15     .12       0   145.3    .045       0
     164     .12       0   414.2      .1       0     550      .1       0
#XS Ineff= 2 ,-1
  202.52  245.84    2032  250.39  297.51 2033.26
Permanent Ineff=
       F       F
Bank Sta=145.3,164
XS Rating Curve= 0 ,0
Exp/Cntr=0.3,0.1

Type RM Length L Ch R = 1 ,1818    ,248.7,249.9,249.2
XS GIS Cut Line= 2
2211749.99227292349023.4254554932211381.94934264348614.714798101
#Sta/Elev= 30
       0 2089.29    33.7 2070.16    53.3 2058.23    63.1 2051.36      68 2046.88
    77.4 2030.06    79.9 2027.07    82.7 2024.37    87.6 2021.71    89.2 2021.45
    97.4 2020.59   107.2 2021.44   112.1 2023.42   121.7  2029.2   126.8 2030.28
   200.7 2030.01   218.7 2029.34   244.5 2030.29   256.5  2029.4   277.4 2031.84
     307 2032.32   344.8 2035.84   430.7  2048.9   452.7 2053.66   470.4 2058.33
   495.8 2066.89   514.2 2075.13   523.3 2080.34   533.8 2084.16     550 2092.43
#Mann= 4 ,-1 , 0
       0      .1       0    89.2    .045       0   107.2     .12       0
     550      .1       0
Bank Sta=89.2,107.2
XS Rating Curve= 0 ,0
Exp/Cntr=0.3,0.1

Type RM Length L Ch R = 1 ,1568    ,261.9,259.6,258.2
XS GIS Cut Line= 2
2211929.00339819  348862.02930262211574.49336045348441.526468915
#Sta/Elev= 30
       0  2093.3      53 2060.15    62.3 2052.09    74.4 2040.22    83.3 2032.05
    93.8 2020.15    95.9 2018.64   100.22016.952     104 2016.03   106.6 2015.98
   113.6  2016.9   124.4 2019.44   134.5 2022.75   141.5 2023.74   151.7 2024.37
     186 2024.11   220.3 2022.44   236.3 2022.77   271.9 2022.31   281.2 2022.82
     319 2023.26   348.7 2029.38   368.7 2032.37   404.9 2039.21   441.9 2046.79
   474.5 2054.54   502.4 2062.28   521.4 2068.27   537.3 2073.95     550 2079.48
#Mann= 4 ,-1 , 0
       0      .1       0   100.2    .045       0   113.6     .12       0
     550      .1       0
Bank Sta=100.2,113.6
XS Rating Curve= 0 ,0
Exp/Cntr=0.3,0.1

Type RM Length L Ch R = 1 ,1308    ,287.8,288.9,284
XS GIS Cut Line= 2
 2212116.6758608348641.9313734732211668.40615415348344.638158461
#Sta/Elev= 30
       0 2071.51    13.9 2062.16    45.8 2042.63    61.5 2033.97    69.4 2030.24
    77.3 2027.15    87.3 2024.05   104.9  2020.2   120.5 2016.01   128.5 2013.41
   132.4 2012.44   141.82013.372     156 2015.62   165.4 2015.61   187.5  2017.4
   215.1 2017.59     253 2021.06   317.4 2023.88   356.8 2024.94   368.6 2024.85
   372.6 2025.31   383.2  2029.1     404  2039.2   431.6 2050.97   439.5  2053.4
   478.8 2063.47   490.7 2066.17   506.3 2070.41   526.1 2078.04   537.9 2083.26
#Mann= 4 ,-1 , 0
       0      .1       0   128.5    .045       0   141.8      .1       0
   537.9      .1       0
#XS Ineff= 2 , 0
                          190.62         2018.19
Permanent Ineff=
       F       F
Bank Sta=128.5,141.8
XS Rating Curve= 0 ,0
Exp/Cntr=0.3,0.1

Type RM Length L Ch R = 1 ,1019    ,207.1,211.5,214.8
XS GIS Cut Line= 2
2212301.37556208348464.1410079982211844.77132781 348207.80178876
#Sta/Elev= 30
       0 2034.52    22.3 2026.99    52.4 2019.51    67.5 2017.41      75 2014.32
    78.8 2013.33   105.7 2010.67   112.6 2010.27   123.9 2010.66   134.9 2012.32
   154.2 2012.86   195.2 2012.24   221.7 2012.78   245.8 2012.57   251.8 2013.12
   260.2 2015.75   266.9 2017.14   278.2 2018.22   289.5 2018.08   315.4 2019.95
   330.8 2019.92   344.6 2020.79   375.8  2021.6   428.7 2030.72   436.2 2033.12
   457.8 2042.94   469.9 2046.38   485.1 2047.32   498.8 2050.48   523.6 2054.42
#Mann= 3 , 0 , 0
       0     .12       0   105.7    .045       0   123.9      .1       0
Bank Sta=105.7,123.9
XS Rating Curve= 0 ,0
Exp/Cntr(USF)=0,0
Exp/Cntr=0.3,0.1

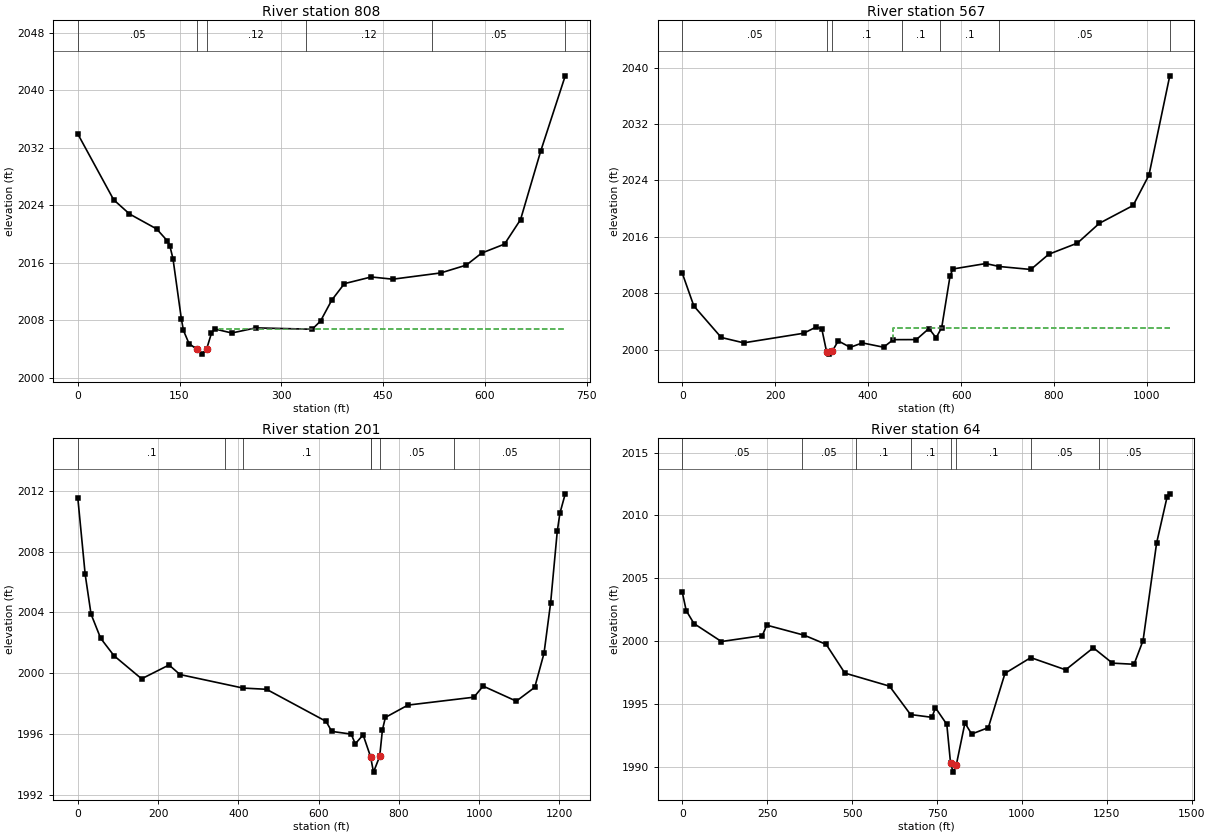
Type RM Length L Ch R = 1 ,808     ,239.1,240.4,240
XS GIS Cut Line= 3
2212458.95080453348422.5460610922212152.07538498347966.117011978
2211988.06625681347928.054875983
#Sta/Elev= 30
       0 2033.92    52.9 2024.76    76.2 2022.79   116.2 2020.71     132 2019.05
   135.6 2018.38   140.3 2016.57   152.6 2008.22   155.7  2006.6   163.9 2004.77
   175.5 2003.98   183.4  2003.3     1902004.048     197 2006.21   201.8  2006.8
   226.9 2006.24   262.5 2006.95   345.5 2006.76   357.8 2007.91   374.3 2010.81
   392.9  2013.1   432.5 2014.03   464.3 2013.72   534.9 2014.59   572.6 2015.68
   595.2 2017.35   628.9  2018.6   652.5    2022   682.2 2031.52   718.4    2042
#Mann= 6 ,-1 , 0
       0     .05       0   175.5    .045       0     190     .12       0
  335.69     .12       0  521.92     .05       0   718.4      .1       0
#XS Ineff= 2 , 0
                          207.83         2006.76
Permanent Ineff=
       F       F
Bank Sta=175.5,190
XS Rating Curve= 0 ,0
Exp/Cntr=0.3,0.1

Type RM Length L Ch R = 1 ,567     ,353,366.3,363.6
XS GIS Cut Line= 4
2212636.70599866348481.6353453162212668.50611461348330.487443615
2212435.52318829347970.2449356952211978.74672029347880.525239727
#Sta/Elev= 30
       0 2010.83    24.8  2006.2    83.8 2001.73   132.1 2000.97   261.2 2002.33
   288.6 2003.23   300.3 2002.91   310.5 1999.71   316.2 1999.37   322.61999.761
   335.5 2001.25   361.3 2000.33   387.4 2000.96   433.2 2000.35   453.8 2001.42
   503.6 2001.43   530.8    2003   546.1 2001.69   558.2 2003.12   576.3 2010.49
   582.4 2011.44   653.1 2012.21   682.3 2011.79     750 2011.37   788.6 2013.53
   850.3 2015.11   897.4 2017.91   970.1 2020.44  1004.2 2024.74    1049 2038.82
#Mann= 7 ,-1 , 0
       0     .05       0   310.5    .045       0   322.6      .1       0
  472.18      .1       0  554.78      .1       0   682.3     .05       0
    1049      .1       0
#XS Ineff= 2 , 0
          288.43  2003.1  454.09         2003.03
Permanent Ineff=
       F       F
Bank Sta=310.5,322.6
XS Rating Curve= 0 ,0
Exp/Cntr=0.3,0.1

Type RM Length L Ch R = 1 ,201     ,133.4,136.5,134.7
XS GIS Cut Line= 4
2212694.48712509348564.5792203512212808.18547064348162.907196306
2212544.33089467 347658.334725572212317.97784965347634.489475579
#Sta/Elev= 30
       0 2011.55    18.4  2006.5      33 2003.89    56.9  2002.3    90.2 2001.15
     159 1999.63   227.4 2000.54   254.6 1999.91   411.7 1999.02   470.2 1998.94
   618.6 1996.83   632.7 1996.17   681.3 1995.99   691.3 1995.35   710.9 1995.94
   729.4 1994.51   736.8 1993.49   752.21994.531     759 1996.27   766.4 1997.09
   822.6  1997.9   986.9 1998.42  1009.9 1999.15  1092.6 1998.16  1138.5 1999.07
  1161.6 2001.31  1178.1 2004.63  1194.6 2009.33  1201.2 2010.52  1214.5  2011.8
#Mann= 7 ,-1 , 0
       0      .1       0  367.05     .05       0   411.7      .1       0
   729.4     .05       0   729.4    .045       0   752.2     .05       0
  938.27     .05       0
Bank Sta=729.4,752.2
XS Rating Curve= 0 ,0
Exp/Cntr=0.3,0.1

Type RM Length L Ch R = 1 ,64      ,79,79,79
XS GIS Cut Line= 6
2212781.15881473348626.0881613882212861.77670653348214.702003121
2212841.62904696347952.2987622592212772.14734344347819.428014462
2212530.46328232347596.2793758442212260.19672322 347549.68169324
#Sta/Elev= 30
       0 2003.88    11.5 2002.43    34.3  2001.4   115.1 1999.97   235.5 2000.44
   248.8 2001.27   359.2 2000.47   423.8 1999.74   478.6 1997.46   610.2 1996.42
   672.2 1994.16     735 1993.94   745.5  1994.7   778.9 1993.38   789.91990.307
   797.4 1989.58   806.8 1990.14   832.3 1993.49   852.1 1992.61   901.2 1993.12
   950.3 1997.44  1026.2 1998.69  1128.9 1997.72  1210.4 1999.47  1266.7 1998.25
  1330.3 1998.16  1356.9 2000.05  1396.8 2007.81  1427.6 2011.47  1435.5 2011.72
#Mann= 8 ,-1 , 0
       0     .05       0  351.71     .05       0  512.78      .1       0
   672.2      .1       0   789.9    .045       0   806.8      .1       0
  1026.2     .05       0 1226.07     .05       0
Bank Sta=789.9,806.8
XS Rating Curve= 0 ,0
Exp/Cntr=0.3,0.1
LCMann Table=0

Chan Stop Cuts=-1
Use User Specified Reach Order=0
Composite Channel Slope=5